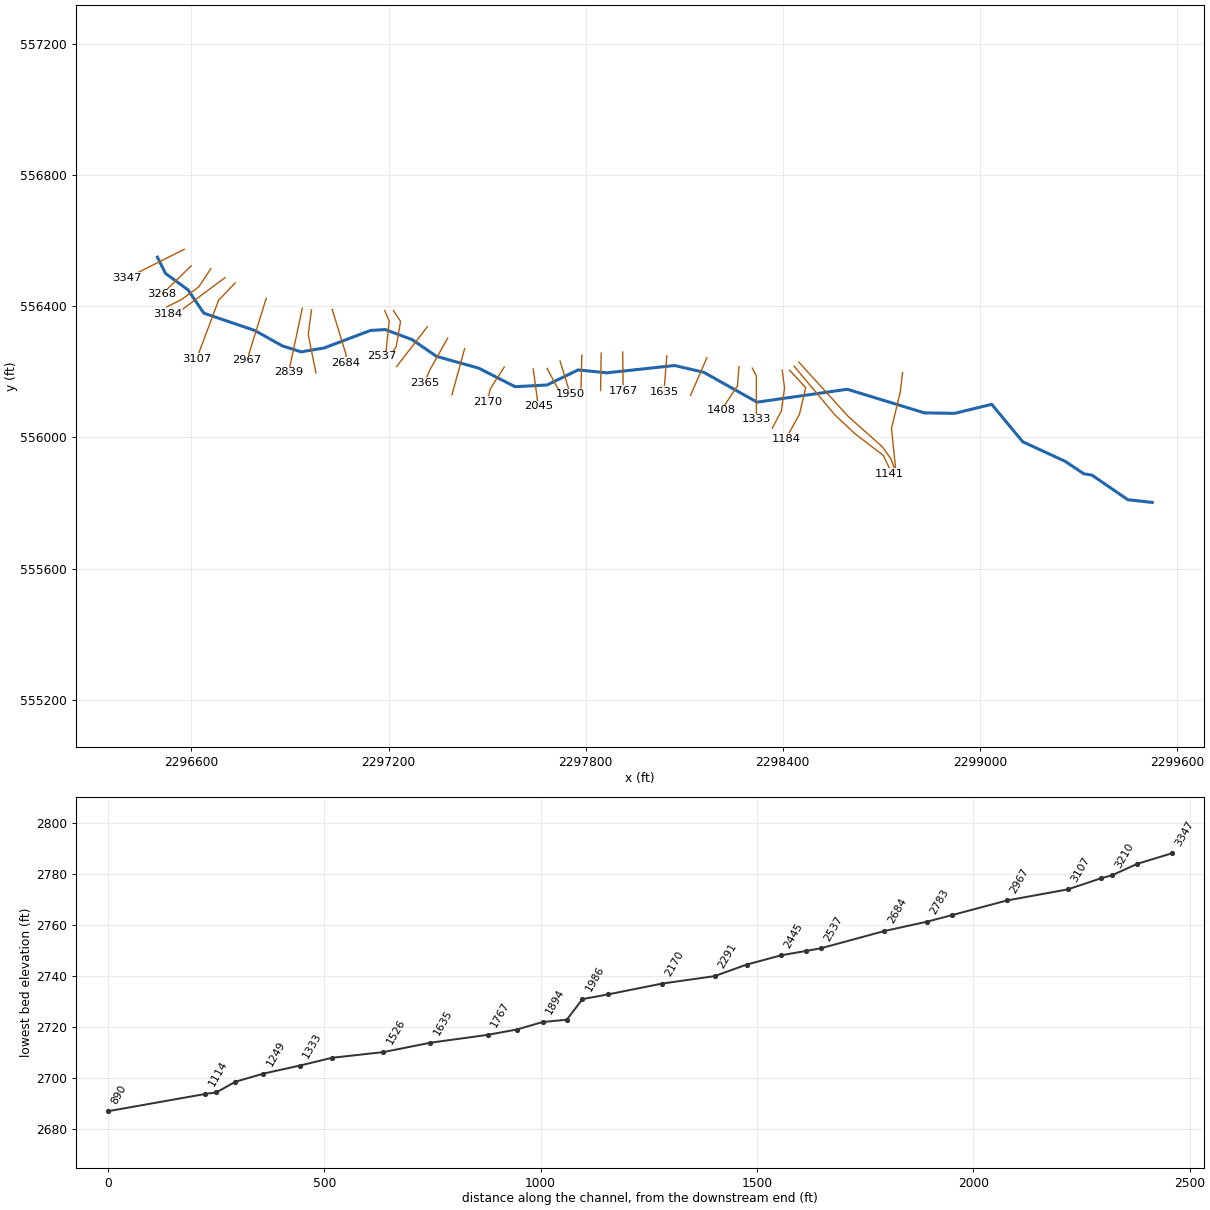
--- ELKCK.prj (project) ---

Proj Title=ELKCK
Current Plan=p01
Default Exp/Contr=0,0
English Units
Geom File=g01
Flow File=f01
Plan File=p01
BEGIN DESCRIPTION:
----------MODEL BY WOOD PLC 2021----------
Stream Name: Elk Creek
Flood Zone: Enhanced Approximate
Pocahontas County, WV
HEC-RAS Version: RAS 6.1
Vertical Datum: NAVD88
Projection: NAD 1983 StatePlane West Virginia S FIPS 4702 (US Feet)
Terrain: 1-meter LIDAR (FEMA Region III 3DEP collected 2016-2018)
Land Use: 2019 NLCD
Hydrologic Method:
WV SIR2010-5033 regression equations
END DESCRIPTION:
DSS File=dss
DSS Export Rating Curves= 0
DSS Export Rating Curve Sorted= 0
DSS Export Volume Flow Curves= 0
DXF OffsetX= 0
DXF OffsetY= 0
DXF ScaleX= 0
DXF ScaleY= 0

--- ELKCK.p01 (plan) ---

Plan Title=Floodplain
Program Version=6.10
Short Identifier=Floodplain
Geom File=g01
Flow File=f01
Subcritical Flow
K Sum by GR= 0
Std Step Tol= 0.01
Critical Tol= 0.01
Num of Std Step Trials= 20
Max Error Tol= 0.3
Flow Tol Ratio= 0.001
Split Flow NTrial= 30
Split Flow Tol= 0.02
Split Flow Ratio= 0.02
Log Output Level= 0
Friction Slope Method= 1
Unsteady Friction Slope Method= 2
Unsteady Bridges Friction Slope Method= 1
Parabolic Critical Depth
Global Vel Dist= 0 , 0 , 0
Global Log Level= 0
CheckData=True
Encroach Param=-1 ,0,0, 0
Computation Interval=0.1SEC
Output Interval=1SEC
Instantaneous Interval=Max Profile
Mapping Interval=1HOUR
Computation Time Step Use Courant=        0
Computation Time Step Use Time Series=    0
Computation Time Step Count To Double=0
Computation Time Step Max Doubling=0
Computation Time Step Max Halving=0
Computation Time Step Residence Courant=0
Run HTab= 0
Run UNet= 0
Run Sediment= 0
Run PostProcess= 0
Run WQNet= 0
Run RASMapper=-1
UNET Theta= 0
UNET Theta Warmup= 0
UNET ZTol= 0
UNET ZSATol= 0
UNET MxIter= 0
UNET Max Iter WO Improvement= 0
UNET MaxInSteps= 0
UNET DtIC= 0
UNET DtMin= 0
UNET MaxCRTS= 0
UNET WFStab= 0
UNET SFStab= 0
UNET WFX= 1
UNET SFX= 1
UNET Gravity=32.174
UNET 1D Methodology=Finite Difference
UNET DSS MLevel= 1
UNET Pardiso=0
UNET DZMax Abort= 0
UNET Use Existing IB Tables= 0
UNET Froude Reduction=False
UNET Froude Limit= 0
UNET Froude Power= 0
UNET D1 Cores= 0
UNET WindReference=Eulerian
UNET WindDragFormulation=Hsu (1988)
UNET D2 Coriolis=0
UNET D2 Cores= 0
UNET D2 Theta= 1
UNET D2 Theta Warmup= 1
UNET D2 Z Tol= 0.01
UNET D2 Volume Tol= 0.01
UNET D2 Max Iterations= 20
UNET D2 Equation= 0
UNET D2 RampUpFraction=0.1
UNET D2 TimeSlices= 1
UNET D2 Turbulence Formulation=Non-Conservative (original)
UNET D2 Eddy Viscosity=0.3
UNET D2 Transverse Eddy Viscosity=0.1
UNET D2 Smagorinsky Mixing=0
UNET D2 BCVolumeCheck=0
UNET D2 Cores=0
UNET D2 SolverType=PARDISO (Direct)
UNET D2 Minimum Iterations= 2147483647
UNET D2 Maximum Iterations= 2147483647
UNET D2 Restart Number= 10
UNET D2 Relaxation Coeff=1.3
UNET D2 SOR Precondition Iterations= 10
UNET D2 ILUT Maximum Fill= 8
UNET D2 ILUT Tolerance=1E-08
UNET D1D2 MaxIter= 0
UNET D1D2 ZTol=0.01
UNET D1D2 QTol=0.1
UNET D1D2 MinQTol=1
DSS File=dss
Write IC File= 0
Write IC File at Fixed DateTime=0
Write IC File at Sim End=0
Echo Input=False
Echo Parameters=False
Echo Output=False
Write Detailed= 0
HDF Write Warmup=0
HDF Write Time Slices=0
HDF Flush=0
HDF Compression= 1
HDF Chunk Size= 1
HDF Spatial Parts= 1
HDF Use Max Rows=0
HDF Fixed Rows= 1
Calibration Method= 0
Calibration Iterations= 20
Calibration Max Change=0.05
Calibration Tolerance=0.2
Calibration Maximum=1.5
Calibration Minimum=0.5
Calibration Optimization Method= 1
WQ AD Non Conservative
WQ ULTIMATE=-1
WQ Max Comp Step=1HOUR
WQ Output Interval=15MIN
WQ Output Selected Increments= 0
WQ Output face flow=0
WQ Output face velocity=0
WQ Output face area=0
WQ Output face dispersion=0
WQ Output cell volume=0
WQ Output cell surface area=0
WQ Output cell continuity=0
WQ Output cumulative cell continuity=0
WQ Output face conc=0
WQ Output face dconc_dx=0
WQ Output face courant=0
WQ Output face peclet=0
WQ Output face adv mass=0
WQ Output face disp mass=0
WQ Output cell mass=0
WQ Output cell source sink temp=0
WQ Output nsm pathways=0
WQ Output nsm derived pathways=0
WQ Create Restart=0
WQ Fixed Restart=0
WQ System Summary=0
WQ Write To DSS=0
Sorting and Armoring Iterations= 10
XS Update Threshold= 0.02
Bed Roughness Predictor= 0
Hydraulics Update Threshold= 0.02
Energy Slope Method= 1
Volume Change Method= 1
Sediment Retention Method= 0
Sediment TS Multiplier= 1
Warm Up Method= 0
XS Weighting Method= 0
Number of US Weighted Cross Sections= 1
Number of DS Weighted Cross Sections= 1
Upstream XS Weight=0
Main XS Weight=1
Downstream XS Weight=0
Number of DS XS's Weighted with US Boundary= 1
Upstream Boundary Weight= 1
Weight of XSs Associated with US Boundary= 0
Number of US XS's Weighted with DS Boundary= 1
Downstream Boundary Weight= 0.5
Weight of XSs Associated with DS Boundary= 0.5
Percentile Method= 0
Sediment Output Level= 3
Mass or Volume Output= 0
Output Increment Type= 1
Profile and TS Output Increment= 1
Transport Output Increment 1
XS Output Flag= 0
XS Output Increment= 10
Read HDF5 Sediment Hotstart= 0
Sediment Hotstart Type= 0
Write Gradation File= 0
Read Gradation Hotstart= 0
Write HDF5 File= 1
Write Binary Output= 1
Write DSS Sediment File= 0
DSS Sediment Output Type= 1
SV Curve= 0
Specific Gage Flag= 0
Subcell Erosion Methods= 0
Subcell Deposition Methods= 0
Advection Scheme= 1
Matrix Solver= 0
Implicit Weighting Factor= 1
Maximum Outer Loop Convergence Iterations= 5
Convergence Maximum Absolute= 0.001
Convergence RMSE= 0.0001
Grain Fractions Max Abs Error= 0.001
Max Subgrid Regions= 1
Max Subgrid Length Scale= 3.402823E+38
Initial Layer Thickness= 3.402823E+38
Min Layer Thickness= 3.402823E+38
Max Layer Thickness= 3.402823E+38
Number of Layers= 5

--- ELKCK.f01 (steady flow) ---

Flow Title=Flow
Program Version=6.10
Number of Profiles= 6
Profile Names=01pct,10pct,04pct,02pct,0_2pct,01plus
River Rch & RM=ELKCK,Main,3347
     973     525     691     827    1350    1440
Boundary for River Rch & Prof#=ELKCK,Main            , 1
Up Type= 0
Dn Type= 3
Dn Slope=0.02769
Boundary for River Rch & Prof#=ELKCK,Main            , 2
Up Type= 0
Dn Type= 3
Dn Slope=0.02769
Boundary for River Rch & Prof#=ELKCK,Main            , 3
Up Type= 0
Dn Type= 3
Dn Slope=0.02769
Boundary for River Rch & Prof#=ELKCK,Main            , 4
Up Type= 0
Dn Type= 3
Dn Slope=0.02769
Boundary for River Rch & Prof#=ELKCK,Main            , 5
Up Type= 0
Dn Type= 3
Dn Slope=0.02769
Boundary for River Rch & Prof#=ELKCK,Main            , 6
Up Type= 0
Dn Type= 3
Dn Slope=0.02769
DSS Import GetInterval= 0
DSS Import GetPeak= 0
DSS Import FillOption= 0

--- ELKCK.g01 (geometry) ---

Geom Title=Geometry
Program Version=6.10

River Reach=ELKCK           ,Main
Reach XY= 30
     2296496.726      556550.284     2296521.502      556500.454
     2296589.538      556450.918     2296637.961      556379.418
     2296793.087      556326.577     2296876.438      556279.723
     2296934.311      556261.305     2297004.751      556273.405
2297144.66005329556326.5514733562297189.67169202 556329.43279218
     2297272.071      556298.604     2297345.763      556247.729
      2297474.75      556211.468     2297585.177      556154.971
     2297682.362      556160.194     2297777.119      556206.178
     2297863.855      556197.274      2298070.63      556219.623
     2298159.042      556199.101     2298321.865      556107.773
     2298596.315      556147.156     2298830.666      556075.171
     2298922.687      556073.576     2299035.755      556101.163
     2299130.096      555986.931     2299259.982      555926.875
     2299316.273      555889.066     2299340.567      555885.219
     2299450.229      555809.939     2299524.345       555801.72

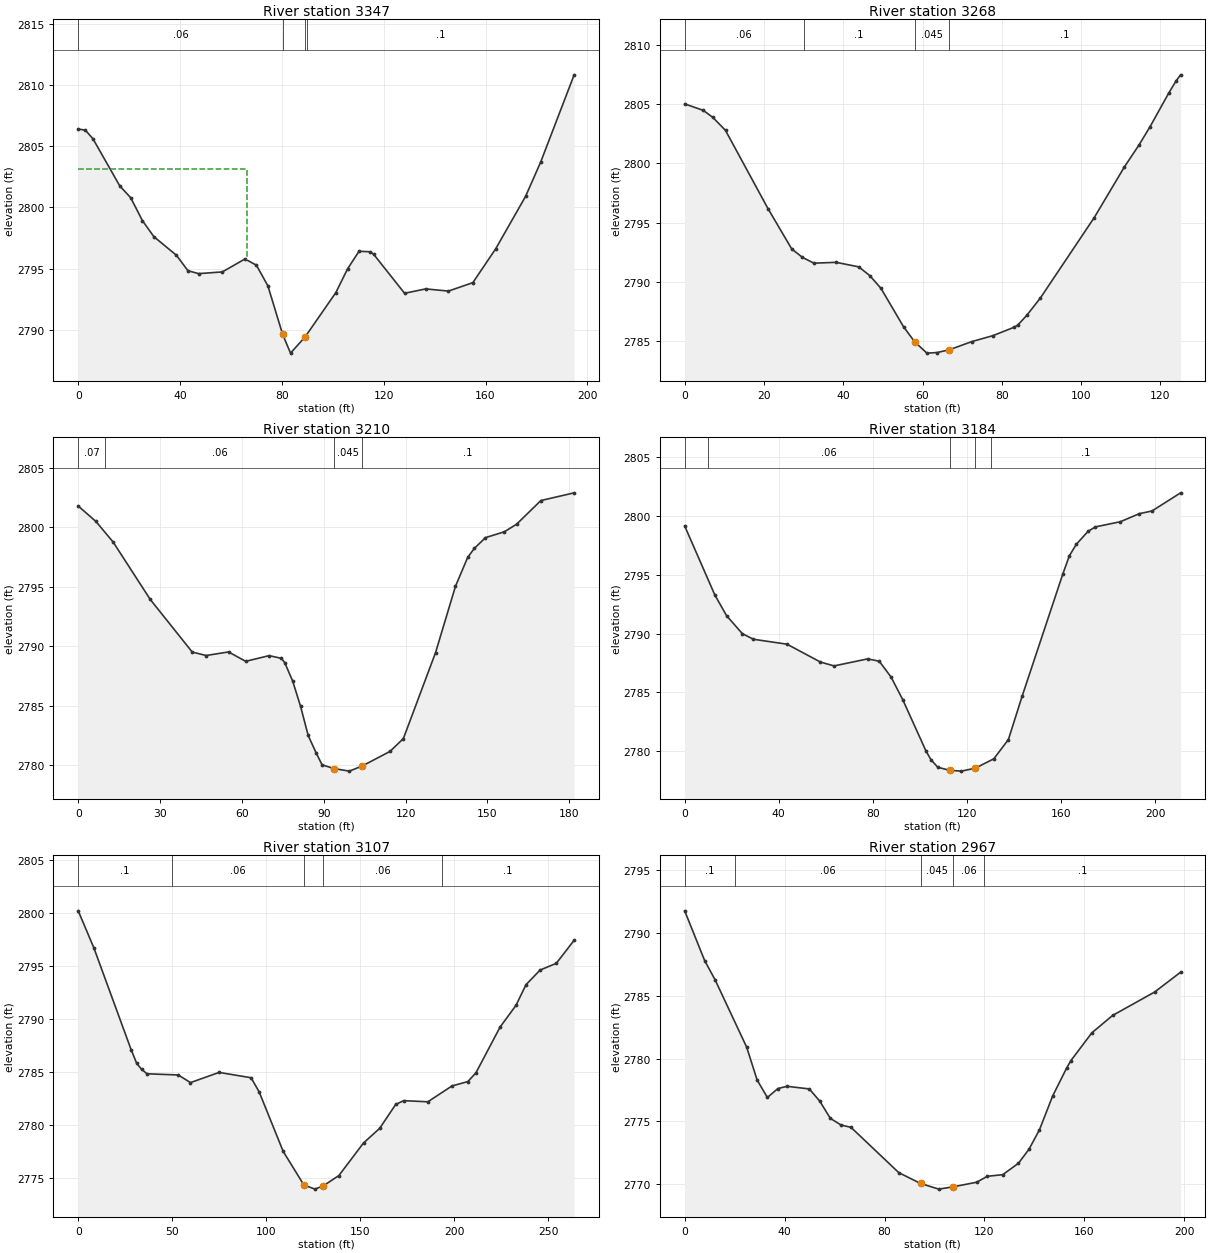
Type RM Length L Ch R = 1 ,3347    ,76.1,79,81.9
XS GIS Cut Line= 2
2296578.72138443556574.4264804862296404.63835376556487.011396416
#Sta/Elev= 30
       0 2806.42     2.8 2806.33     5.8 2805.62    16.3 2801.77    20.6  2800.8
    25.2 2798.93    29.7 2797.61    38.6 2796.08    43.1 2794.82    47.3 2794.58
    56.6 2794.72    65.5 2795.78      70 2795.27    74.5 2793.58    80.3  2789.6
    83.4 2788.07    89.2 2789.42   101.2 2793.03   105.8 2794.97   110.3 2796.41
   114.7 2796.37   116.1 2796.15   128.2 2792.97   136.5 2793.33   145.4 2793.15
     155 2793.84     164 2796.62   175.7  2800.9   181.6 2803.69   194.8 2810.86
#Mann= 4 ,-1,0
       0     .06       0    80.3    .045       0    89.2     .06       0
      90      .1       0
#XS Ineff= 2 , 0
           66.47 2803.17
Permanent Ineff=
       F       F
Bank Sta=80.3,89.2
XS Rating Curve= 0 ,0
Exp/Cntr(USF)=0,0
Exp/Cntr=0.3,0.1

Type RM Length L Ch R = 1 ,3268    ,59.7,58.6,56.9
XS GIS Cut Line= 2
2296599.51720878556523.8803891812296510.08485354556436.465305111
#Sta/Elev= 30
       0 2805.03     4.7 2804.48     7.1 2803.89    10.3 2802.79      21  2796.2
      27 2792.79    29.7 2792.08    32.6 2791.59    38.2 2791.66    43.9 2791.28
    46.7 2790.54    49.5 2789.47    55.2 2786.23      58 2784.96    61.1    2784
    63.7 2784.05    66.8 2784.29    72.5 2784.98    77.8 2785.48      83 2786.17
      84 2786.36    86.3 2787.19    89.7 2788.64   103.3 2795.43   110.9  2799.7
   114.6 2801.56   117.4 2803.11   122.1 2805.94     124 2806.99   125.1 2807.48
#Mann= 4 ,-1,0
       0     .06       0      30      .1       0      58    .045       0
    66.8      .1       0
Bank Sta=58,66.8
XS Rating Curve= 0 ,0
Exp/Cntr(USF)=0,0
Exp/Cntr=0.3,0.1

Type RM Length L Ch R = 1 ,3210    ,25.7,25.7,26
XS GIS Cut Line= 4
2296659.22340199556515.173392088 2296622.5232682556459.555663572
2296570.68905864556421.3421222112296525.28683128556398.641008531
#Sta/Elev= 30
       0  2801.8     6.5  2800.5    12.8 2798.77    26.4 2793.94    41.8 2789.51
    46.9 2789.22    55.1 2789.52    61.4 2788.73      70 2789.21    74.5 2788.98
    75.7 2788.62    78.6 2787.08    81.5 2784.95    84.3 2782.49    87.2 2781.03
    89.4 2780.02    93.82779.703    99.4 2779.49   104.1 2779.92   114.3 2781.15
   119.2 2782.23     131 2789.47   138.3 2795.05   142.8 2797.49   145.2 2798.23
   149.3 2799.14   156.2 2799.63   160.7 2800.27   169.6 2802.26   181.8 2802.91
#Mann= 4 ,-1,0
       0     .07       0      10     .06       0    93.8    .045       0
   104.1      .1       0
Bank Sta=93.8,104.1
XS Rating Curve= 0 ,0
Exp/Cntr(USF)=0,0
Exp/Cntr=0.3,0.1

Type RM Length L Ch R = 1 ,3184    ,71,76.7,82.7
XS GIS Cut Line= 3
 2296702.3920614556487.8414661452296562.80959771556383.525385351
2296527.07774818556375.651303547
#Sta/Elev= 30
       0 2799.17    12.8  2793.3    17.8 2791.53    24.5    2790    29.2 2789.52
    43.5  2789.1    57.7 2787.58    63.5 2787.25    77.8 2787.85    82.7 2787.65
    87.7 2786.31    92.7 2784.37   102.6 2779.99   104.7 2779.26   107.6 2778.62
   112.6 2778.36   117.6 2778.29   123.5 2778.54   131.4 2779.34   137.6 2780.98
   143.5 2784.71   160.7 2795.06   163.5 2796.62   166.4 2797.59   171.5 2798.72
   174.6 2799.09   185.2 2799.53   193.3 2800.22   198.6 2800.44   210.8 2801.99
#Mann= 5 ,-1,0
       0      .1       0      10     .06       0   112.6    .045       0
   123.5     .06       0     130      .1       0
Bank Sta=112.6,123.5
XS Rating Curve= 0 ,0
Exp/Cntr(USF)=0,0
Exp/Cntr=0.3,0.1

Type RM Length L Ch R = 1 ,3107    ,139.4,140.1,140.6
XS GIS Cut Line= 3
2296733.28918436556471.7608263642296682.63550526556418.383831183
2296616.18659289556240.278959509
#Sta/Elev= 30
       0 2800.17     8.3 2796.69    28.1  2787.1    31.1 2785.79    33.7 2785.23
    36.6 2784.81    53.2  2784.7    59.7 2783.98    74.9 2784.94    91.9 2784.44
    96.2 2783.11     109 2777.49     120 2774.33   125.9 2773.94   130.4 2774.26
   138.6 2775.22   151.7 2778.29   160.3 2779.67   168.8 2781.92   173.1 2782.28
   185.9 2782.17   198.7 2783.66   207.2 2784.08   211.5 2784.91   224.3 2789.21
   232.8 2791.27   238.1 2793.21   245.6 2794.59   254.2 2795.22   263.7  2797.4
#Mann= 5 ,-1,0
       0      .1       0      50     .06       0     120    .045       0
   130.4     .06       0  193.59      .1       0
Bank Sta=120,130.4
XS Rating Curve= 0 ,0
Exp/Cntr(USF)=0,0
Exp/Cntr=0.3,0.1

Type RM Length L Ch R = 1 ,2967    ,128,128,128.5
XS GIS Cut Line= 2
2296827.83602552556424.8283312732296769.01239817 556235.28553206
#Sta/Elev= 30
       0 2791.75       8 2787.79    12.2 2786.25    24.8 2780.91      29 2778.29
    33.1  2776.9    37.3 2777.61      41 2777.79    49.9 2777.58    54.1  2776.6
    58.3 2775.24    62.5 2774.72    66.6 2774.52    85.7 2770.92    94.42770.063
   101.7 2769.61   107.52769.795   116.9 2770.16   121.1 2770.63   127.3 2770.76
   133.6 2771.67   137.8 2772.78     142 2774.33   147.3 2777.03   152.9 2779.25
   154.6 2779.84     163 2782.05   171.3 2783.43   188.1 2785.29   198.5 2786.87
#Mann= 5 ,-1,0
       0      .1       0      20     .06       0    94.4    .045       0
   107.5     .06       0     120      .1       0
Bank Sta=94.4,107.5
XS Rating Curve= 0 ,0
Exp/Cntr(USF)=0,0
Exp/Cntr=0.3,0.1

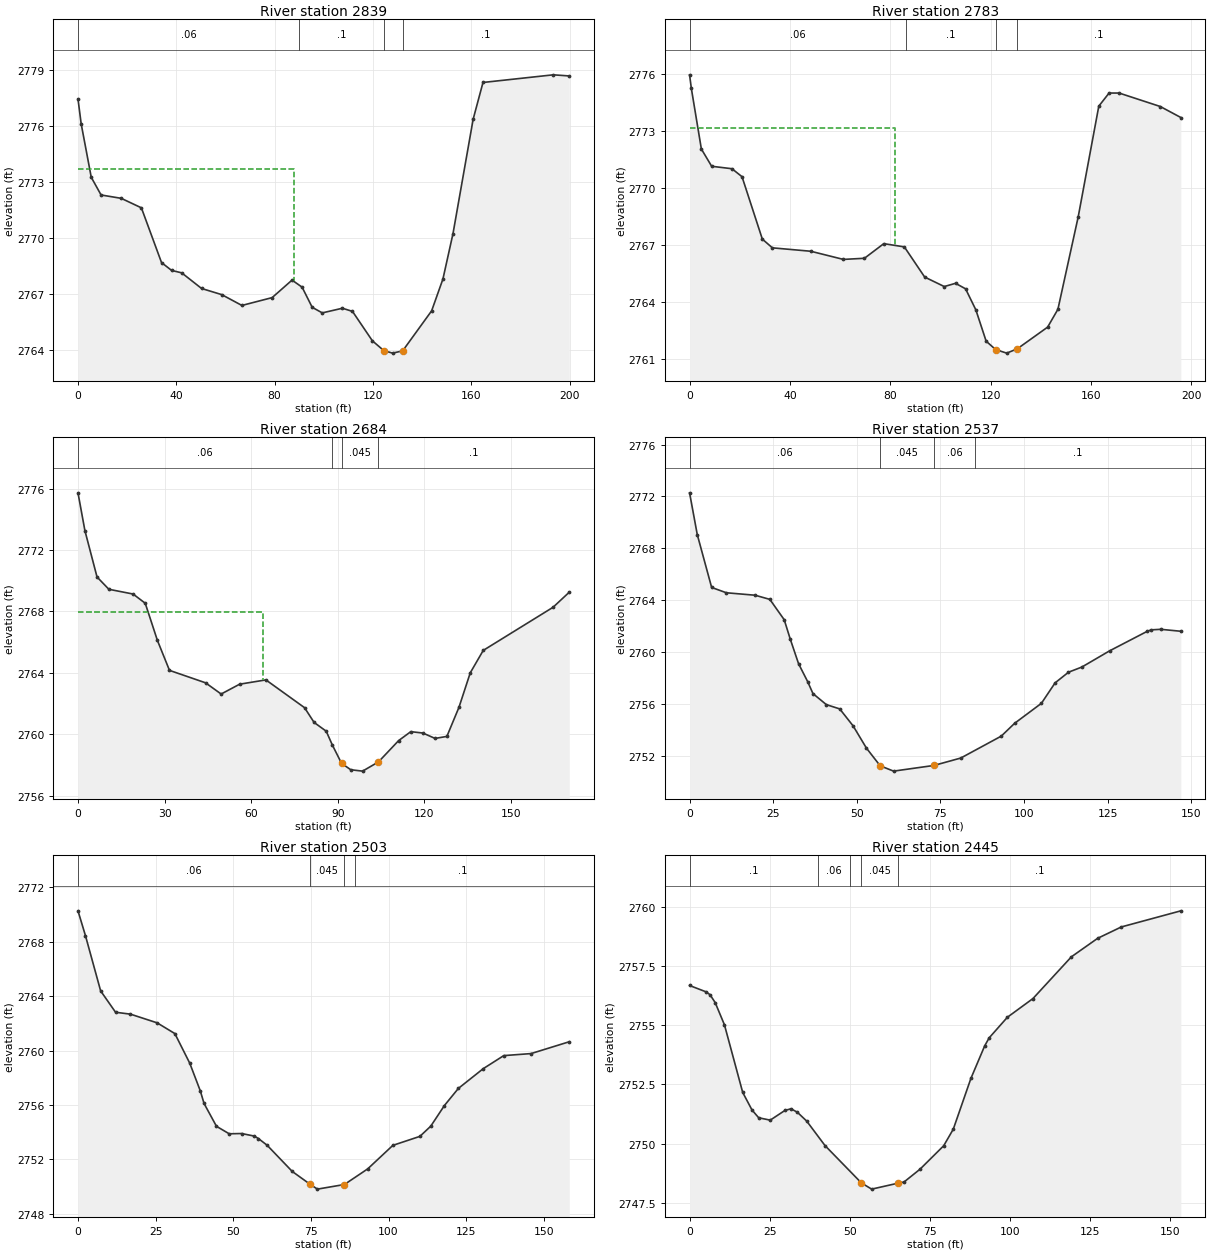
Type RM Length L Ch R = 1 ,2839    ,52.4,56.5,59.9
XS GIS Cut Line= 2
2296937.53789041556394.4186496732296896.08296785556198.864382371
#Sta/Elev= 30
       0 2777.47     1.3 2776.13     5.4 2773.26     9.4 2772.31    17.6 2772.13
    25.8 2771.62      34 2768.68    38.1 2768.26    42.2 2768.13    50.3 2767.29
    58.5 2766.96    66.7 2766.38      79  2766.8    87.1 2767.74    91.2 2767.36
    95.3 2766.28    99.4 2765.98   107.6 2766.23   111.7 2766.06   119.8 2764.48
   124.4 2763.96     128 2763.82   132.1 2763.94   143.9 2766.09   148.5  2767.8
   152.6 2770.24   160.8 2776.38   164.8 2778.35   193.4 2778.76   199.9  2778.7
#Mann= 4 ,-1,0
       0     .06       0      90      .1       0   124.4    .045       0
   132.1      .1       0
#XS Ineff= 2 , 0
           87.75 2773.71
Permanent Ineff=
       F       F
Bank Sta=124.4,132.1
XS Rating Curve= 0 ,0
Exp/Cntr(USF)=0,0
Exp/Cntr=0.3,0.1

Type RM Length L Ch R = 1 ,2783    ,97.8,99.1,99.5
XS GIS Cut Line= 3
2296965.81133945556389.8834961412296955.63105849556314.167656511
2296979.17295821556197.094425485
#Sta/Elev= 30
       0 2775.96      .7 2775.25     4.7 2772.05     8.8 2771.14    16.9 2771.01
    20.9 2770.59      29  2767.3      33 2766.84    48.3 2766.66    61.3 2766.23
    69.7 2766.29    77.4 2767.06    85.6 2766.89    93.7  2765.3   101.5  2764.8
     106 2764.97     110 2764.68   114.1 2763.57   118.2 2761.92     1222761.476
   126.4 2761.29   130.62761.516   142.7 2762.66   146.8  2763.6   154.9 2768.48
   163.1 2774.31   167.2    2775   171.2    2775   187.6 2774.29   195.8 2773.71
#Mann= 4 ,-1,0
       0     .06       0    86.4      .1       0     122    .045       0
   130.6      .1       0
#XS Ineff= 2 , 0
           81.73 2773.15
Permanent Ineff=
       F       F
Bank Sta=122,130.6
XS Rating Curve= 0 ,0
Exp/Cntr(USF)=0,0
Exp/Cntr=0.3,0.1

Type RM Length L Ch R = 1 ,2684    ,151.4,147.2,141.2
XS GIS Cut Line= 3
2297028.49485118556391.4523225322297070.87026338 556252.59717719
2297069.35685581556227.625952142
#Sta/Elev= 30
       0 2775.72     2.4 2773.26     6.6 2770.24    10.7 2769.44    19.1 2769.13
    23.3 2768.53    27.5 2766.12    31.7 2764.16    44.2 2763.35    49.6 2762.62
      56 2763.26    65.1 2763.54    78.5 2761.73    81.8 2760.77      86  2760.2
    88.1 2759.31    91.3 2758.11    94.5 2757.69    98.6  2757.6   104.1  2758.2
   111.1 2759.59   115.3 2760.17   119.5 2760.08   123.7 2759.73   127.8 2759.86
     132 2761.76   135.9    2764   140.4 2765.46   164.6 2768.27   170.2 2769.25
#Mann= 4 ,-1,0
       0     .06       0    88.1      .1       0    91.3    .045       0
   104.1      .1       0
#XS Ineff= 2 , 0
           63.99 2767.97
Permanent Ineff=
       F       F
Bank Sta=91.3,104.1
XS Rating Curve= 0 ,0
Exp/Cntr(USF)=0,0
Exp/Cntr=0.3,0.1

Type RM Length L Ch R = 1 ,2537    ,34.1,33.1,31.5
XS GIS Cut Line= 4
2297188.53770262556387.2904516912297202.15837083 556354.75218875
2297192.69957347556266.2178453982297178.70055336556248.435306349
#Sta/Elev= 30
       0 2772.28     2.3 2769.06     6.6 2764.98      11 2764.57    19.6 2764.38
      24 2764.06    28.3 2762.49    30.1    2761    32.6 2759.09    35.3 2757.72
    36.9 2756.79    40.9 2755.94    44.9 2755.61    48.9  2754.3    52.9 2752.58
      57 2751.22      61 2750.81    73.1 2751.25    81.1 2751.82    93.2 2753.51
    97.2  2754.5   105.2 2756.04   109.3 2757.62   113.3 2758.44   117.3 2758.84
   125.6 2760.09   136.8 2761.59   138.1 2761.71   140.9 2761.75   146.9  2761.6
#Mann= 4 ,-1,0
       0     .06       0      57    .045       0    73.1     .06       0
   85.27      .1       0
Bank Sta=57,73.1
XS Rating Curve= 0 ,0
Exp/Cntr(USF)=0,0
Exp/Cntr=0.3,0.1

Type RM Length L Ch R = 1 ,2503    ,62.7,58.1,52.4
XS GIS Cut Line= 4
2297215.02233525556387.2904516912297236.58839325556354.373836855
2297223.34607693556276.8116984492297200.26661136556243.895083613
#Sta/Elev= 30
       0 2770.28     2.4 2768.46     7.3 2764.39    12.1 2762.82    16.9 2762.68
    25.5 2762.04    31.2 2761.25      36 2759.07    39.4 2757.03    40.6 2756.11
    44.6 2754.43    48.7 2753.88    52.7  2753.9    56.8 2753.71    58.1 2753.53
    60.9 2753.04      69 2751.11    74.6 2750.19    77.1 2749.81    85.8 2750.15
    93.3  2751.3   101.4 2753.03   110.1 2753.69   113.6 2754.44     118 2755.96
   122.5 2757.22   130.5 2758.67   137.1 2759.63   145.9 2759.78   158.2 2760.65
#Mann= 4 ,-1,0
       0     .06       0    74.6    .045       0    85.8     .06       0
   89.35      .1       0
Bank Sta=74.6,85.8
XS Rating Curve= 0 ,0
Exp/Cntr(USF)=0,0
Exp/Cntr=0.3,0.1

Type RM Length L Ch R = 1 ,2445    ,78.3,79.9,81.2
XS GIS Cut Line= 2
2297318.33816933556338.2914414632297224.87127175556216.582747488
#Sta/Elev= 30
       0 2756.67     5.2  2756.4     6.4 2756.28       8 2755.95    10.9 2755.01
    16.6 2752.16    19.5 2751.42    21.6 2751.09    25.2 2750.99    29.8  2751.4
    31.7 2751.47    33.7 2751.32    36.6 2750.95    42.3 2749.92    53.7 2748.34
    56.9 2748.08    65.1 2748.33      67 2748.38      72 2748.92    79.4 2749.91
    82.4 2750.61    87.9 2752.75    92.2 2754.12    93.6 2754.46    99.3 2755.33
   107.3 2756.12   119.3 2757.88   127.5 2758.66   134.9 2759.14   153.5 2759.82
#Mann= 5 ,-1,0
       0      .1       0      40     .06       0      50      .1       0
    53.7    .045       0    65.1      .1       0
Bank Sta=53.7,65.1
XS Rating Curve= 0 ,0
Exp/Cntr(USF)=0,0
Exp/Cntr=0.3,0.1

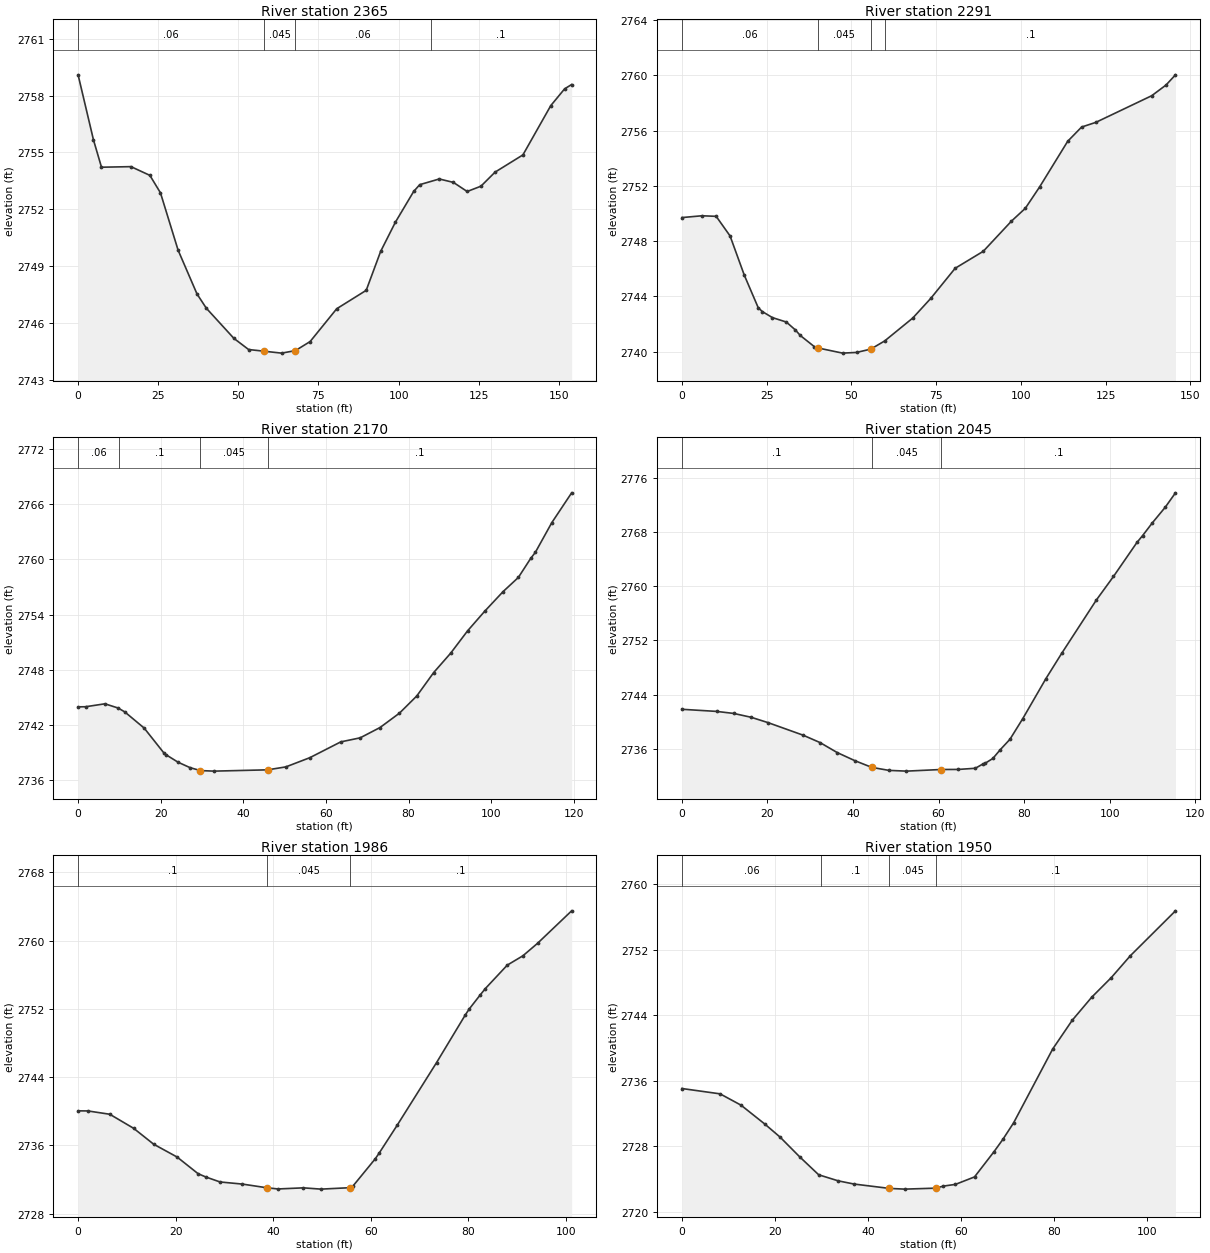
Type RM Length L Ch R = 1 ,2365    ,71.1,74.1,76.3
XS GIS Cut Line= 3
2297380.26220133556303.582111508 2297325.6113721556205.957980662
2297309.26283344556167.188588987
#Sta/Elev= 30
       0 2759.09     4.8 2755.66     7.3 2754.22    16.5 2754.25    22.4 2753.79
    25.7 2752.87    31.2 2749.85    37.1 2747.54      40 2746.79    48.6  2745.2
    53.2 2744.61    58.1 2744.52    63.5 2744.42    67.82744.552    72.4 2745.03
    80.7 2746.76    89.9 2747.73    94.4 2749.78      99 2751.32   104.7 2752.94
   106.6  2753.3   112.7  2753.6   117.1 2753.42   121.4 2752.94   125.7 2753.22
   130.1 2753.96   138.8 2754.87   147.5 2757.47   151.8 2758.35     154 2758.58
#Mann= 4 ,-1,0
       0     .06       0    58.1    .045       0    67.8     .06       0
     110      .1       0
Bank Sta=58.1,67.8
XS Rating Curve= 0 ,0
Exp/Cntr(USF)=0,0
Exp/Cntr=0.3,0.1

Type RM Length L Ch R = 1 ,2291    ,125.8,121.5,118
XS GIS Cut Line= 2
2297431.60124353 556270.880508972297393.06329952  556130.4282308
#Sta/Elev= 30
       0 2749.71     5.9 2749.84    10.1  2749.8    14.2 2748.38    18.4 2745.54
    22.5 2743.19    23.7 2742.91    26.7 2742.47    30.8 2742.15    33.5 2741.57
    34.9 2741.18    39.1 2740.36      40 2740.28    47.4  2739.9    51.5 2739.95
    55.7 2740.19    59.8 2740.78    68.1 2742.44    73.4 2743.86    80.6 2746.04
    88.9 2747.27    97.2 2749.45   101.3 2750.38   105.5 2751.92   113.8 2755.23
   117.9 2756.26   122.1  2756.6   138.6 2758.53   142.8  2759.3   145.6 2760.04
#Mann= 4 ,-1,0
       0     .06       0      40    .045       0    55.7     .06       0
      60      .1       0
Bank Sta=40,55.7
XS Rating Curve= 0 ,0
Exp/Cntr(USF)=0,0
Exp/Cntr=0.3,0.1

Type RM Length L Ch R = 1 ,2170    ,113.5,124.6,132.1
XS GIS Cut Line= 3
2297552.12819979556214.692804817 2297509.7584612556148.550406157
2297501.07067883556108.575368183
#Sta/Elev= 30
       0 2743.96     1.8 2743.97     6.5 2744.29     9.7 2743.83    11.3 2743.41
      16 2741.65    20.8 2738.93    21.3 2738.75    24.2 2737.94    27.1 2737.35
    29.6 2737.03    32.9 2736.97    45.9 2737.11    50.3 2737.43    56.1 2738.43
    63.6 2740.15    68.3 2740.59    73.1 2741.71    77.8 2743.27      82 2745.14
    86.1 2747.69    90.2 2749.79    94.3 2752.22    98.4 2754.33   102.9 2756.49
   106.6 2758.03   109.6 2760.11   110.7 2760.75   114.7 2763.99   119.5 2767.23
#Mann= 4 ,-1,0
       0     .06       0      10      .1       0    29.6    .045       0
    45.9      .1       0
Bank Sta=29.6,45.9
XS Rating Curve= 0 ,0
Exp/Cntr(USF)=0,0
Exp/Cntr=0.3,0.1

Type RM Length L Ch R = 1 ,2045    ,54.2,59,63.8
XS GIS Cut Line= 2
2297640.42913294556209.1860865292297655.89487859556094.874053514
#Sta/Elev= 30
       0 2741.84     8.1 2741.53    12.1 2741.23    16.2 2740.66    20.2 2739.86
    28.3 2738.03    32.3 2736.93    36.3 2735.46    40.4 2734.27    44.4 2733.27
    48.4 2732.83    52.5 2732.72    60.6 2732.96    64.6 2732.97    68.6 2733.14
    70.3 2733.75    70.9 2733.88    72.7 2734.59    74.4 2735.86    76.7 2737.42
    79.7 2740.47    85.1 2746.36    88.8  2750.1    96.9 2757.96   100.9 2761.43
   106.4 2766.46   107.7 2767.45     110 2769.35     113 2771.64   115.4 2773.77
#Mann= 3 ,0,0
       0      .1       0    44.4    .045       0    60.6      .1       0
Bank Sta=44.4,60.6
XS Rating Curve= 0 ,0
Exp/Cntr(USF)=0,0
Exp/Cntr=0.3,0.1

Type RM Length L Ch R = 1 ,1986    ,38.4,36.3,34.4
XS GIS Cut Line= 2
2297682.48987509556210.9039992772297730.01906182556121.572033864
#Sta/Elev= 28
       0 2740.05       2 2740.04     6.5 2739.65    11.4    2738    15.5 2736.14
    20.3 2734.64    24.6 2732.69    26.2  2732.3    29.1 2731.72    33.7 2731.47
    38.8 2731.03      41  2730.9    46.2 2731.03    49.8 2730.88    55.8 2731.05
    56.3  2731.2    60.9 2734.41    61.7 2735.07    65.4 2738.34    73.5  2745.7
    79.4 2751.29    80.2 2751.98    82.4 2753.59    83.5 2754.37      88 2757.12
    91.2 2758.21    94.2 2759.67   101.2 2763.48
#Mann= 3 ,0,0
       0      .1       0    38.8    .045       0    55.8      .1       0
Bank Sta=38.8,55.8
XS Rating Curve= 0 ,0
Exp/Cntr(USF)=0,0
Exp/Cntr=0.3,0.1

Type RM Length L Ch R = 1 ,1950    ,59.7,55.8,53.3
XS GIS Cut Line= 2
 2297722.0138741556233.3012305622297753.41708136556131.902922792
#Sta/Elev= 24
       0 2735.07     8.2 2734.42    12.7 2733.04    17.8 2730.74    21.1 2729.14
    25.3 2726.74    29.4 2724.54    33.6  2723.8      37 2723.41    44.62722.878
    47.9 2722.79    54.6 2722.91    56.2 2723.16    58.8 2723.37    62.9 2724.28
    67.1 2727.37      69 2728.87    71.3 2730.88    79.7 2739.89    83.9  2743.4
    88.1 2746.22    92.3 2748.61    96.4 2751.28   106.1 2756.76
#Mann= 4 ,-1,0
       0     .06       0      30      .1       0    44.6    .045       0
    54.6      .1       0
Bank Sta=44.6,54.6
XS Rating Curve= 0 ,0
Exp/Cntr(USF)=0,0
Exp/Cntr=0.3,0.1

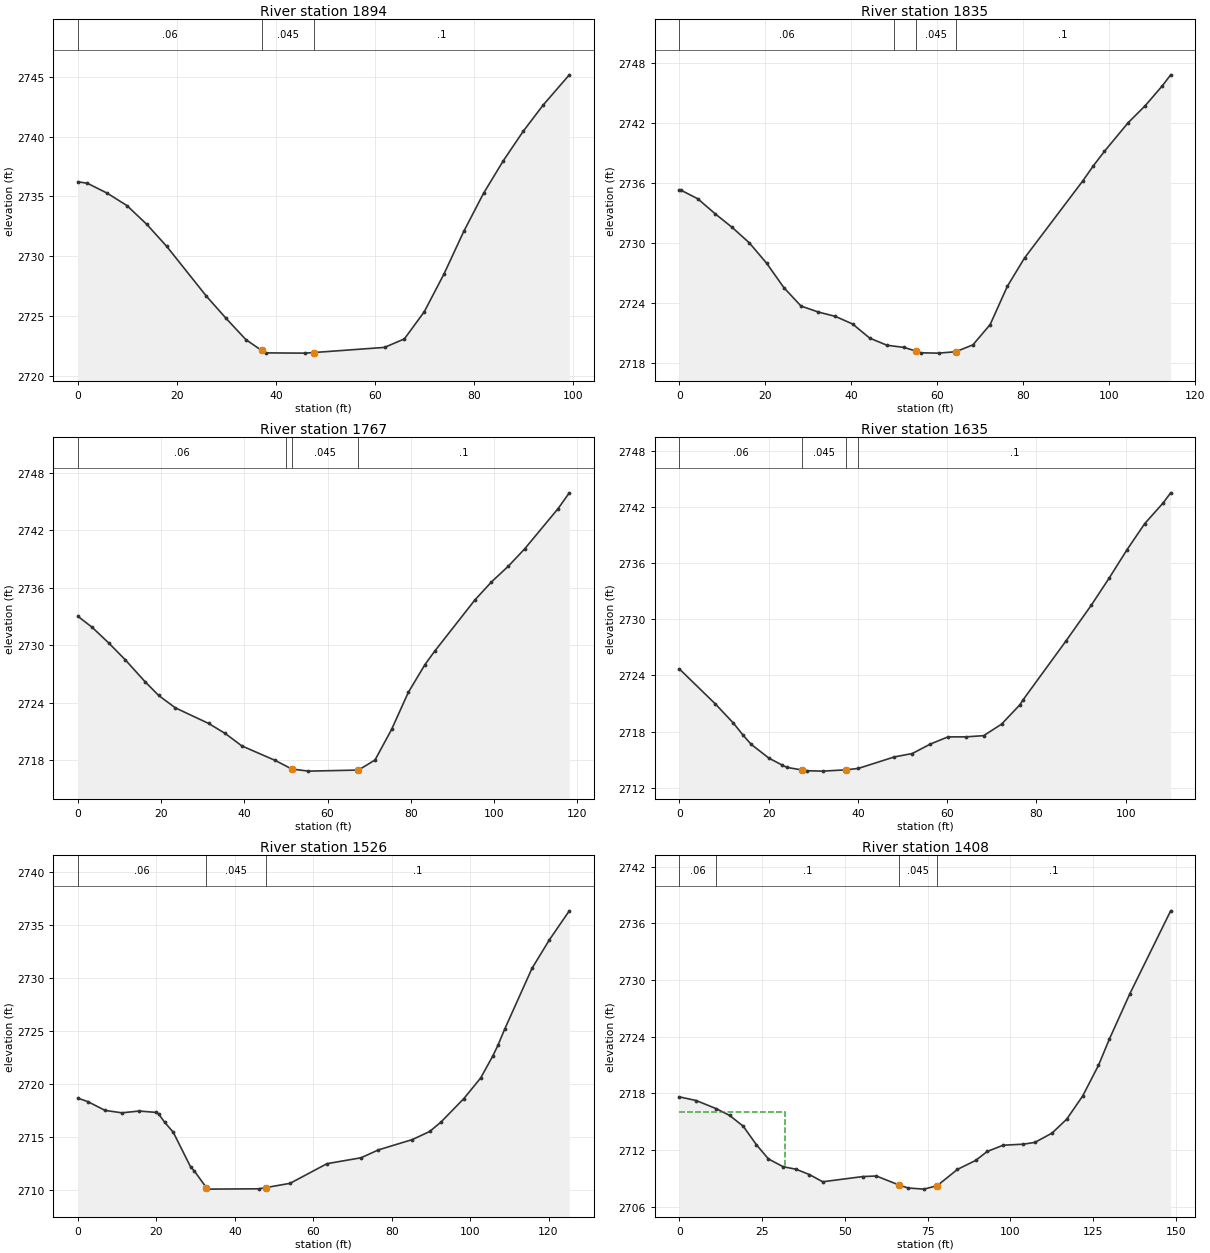
Type RM Length L Ch R = 1 ,1894    ,60.1,59.7,60
XS GIS Cut Line= 2
2297788.22545567556251.083769611 2297785.9553443556151.955573209
#Sta/Elev= 23
       0 2736.21     1.9 2736.09     5.9 2735.26     9.9 2734.22    13.9 2732.65
    17.9 2730.82    25.9 2726.66    29.9 2724.79    33.9 2723.01    37.1  2722.1
    37.9  2721.9    45.9 2721.88    47.72721.932    61.9 2722.36    65.9 2723.07
    69.9 2725.33    73.9  2728.5    77.9 2732.07    81.9 2735.26    85.9 2737.99
    89.9 2740.44    93.9 2742.62    99.2 2745.16
#Mann= 3 ,0,0
       0     .06       0    37.1    .045       0    47.7      .1       0
Bank Sta=37.1,47.7
XS Rating Curve= 0 ,0
Exp/Cntr(USF)=0,0
Exp/Cntr=0.3,0.1

Type RM Length L Ch R = 1 ,1835    ,67.5,67.5,67.7
XS GIS Cut Line= 2
2297847.24835124556257.5157518212297845.35659176556143.253479632
#Sta/Elev= 30
       0 2735.25      .3 2735.28     4.3  2734.4     8.3 2732.91    12.3 2731.53
    16.3 2729.98    20.3 2727.95    24.3 2725.51    28.3 2723.66    32.3 2723.06
    36.3 2722.62    40.3 2721.86    44.3 2720.44    48.3 2719.73    52.3 2719.51
      552719.146    56.3 2718.97    60.3 2718.94    64.3 2719.08    68.3 2719.77
    72.3  2721.8    76.3 2725.63    80.3 2728.47    93.9 2736.22    96.3  2737.7
    98.9 2739.16   104.4 2742.02   108.4 2743.74   112.4 2745.74   114.3 2746.82
#Mann= 4 ,-1,0
       0     .06       0      50      .1       0      55    .045       0
    64.3      .1       0
Bank Sta=55,64.3
XS Rating Curve= 0 ,0
Exp/Cntr(USF)=0,0
Exp/Cntr=0.3,0.1

Type RM Length L Ch R = 1 ,1767    ,132.7,131.9,131.5
XS GIS Cut Line= 2
2297912.70322901556260.5425669782297914.21663659556142.496775842
#Sta/Elev= 25
       0    2733     3.4 2731.86     7.4 2730.22    11.4 2728.45    16.1 2726.19
    19.4 2724.74    23.4 2723.45    31.4 2721.82    35.4 2720.77    39.4 2719.47
    47.4 2717.96    51.4 2717.06    55.4 2716.84    67.4 2716.95    71.4    2718
    75.4 2721.21    79.4 2725.06    83.4 2727.96    85.7 2729.34    95.4 2734.71
    99.4  2736.6   103.4 2738.22   107.4 2740.06   115.4 2744.25   118.1  2745.9
#Mann= 4 ,-1,0
       0     .06       0      50      .1       0    51.4    .045       0
    67.4      .1       0
Bank Sta=51.4,67.4
XS Rating Curve= 0 ,0
Exp/Cntr(USF)=0,0
Exp/Cntr=0.3,0.1

Type RM Length L Ch R = 1 ,1635    ,114.3,109.1,106.3
XS GIS Cut Line= 2
2298047.01815162556249.1920101382298038.31605804556139.469960685
#Sta/Elev= 29
       0 2724.69       8 2720.98    12.1 2718.91    14.3  2717.6    16.1 2716.63
    20.1 2715.15    23.1  2714.4    24.1 2714.17    27.4  2713.9    28.7 2713.81
    32.1 2713.77    37.32713.906    40.1 2714.06    48.2 2715.29    52.2 2715.65
    56.2 2716.65    60.2 2717.43    64.2 2717.43    68.2 2717.56    72.2 2718.79
    76.3 2720.85      77 2721.37    86.6 2727.65    92.3 2731.49    96.3 2734.38
   100.3 2737.41   104.3 2740.22   108.4 2742.41   110.1  2743.5
#Mann= 4 ,-1,0
       0     .06       0    27.4    .045       0    37.3     .06       0
      40      .1       0
Bank Sta=27.4,37.3
XS Rating Curve= 0 ,0
Exp/Cntr(USF)=0,0
Exp/Cntr=0.3,0.1

Type RM Length L Ch R = 1 ,1526    ,120.3,117.8,116.1
XS GIS Cut Line= 2
2298168.95417971556243.4796964332298119.19482416556128.495239695
#Sta/Elev= 30
       0 2718.65     2.5 2718.33     6.9  2717.5    11.2 2717.27    15.6 2717.44
    19.9 2717.31    20.6 2717.15    22.1 2716.38    24.3 2715.44    28.7 2712.18
    29.7 2711.77   32.76  2710.2      33 2710.07    46.1  2710.1      48 2710.22
    54.1 2710.62    63.5 2712.47    72.2 2713.03    76.6 2713.77    85.3 2714.75
    89.7 2715.51    92.6 2716.41    98.4 2718.61   102.7 2720.56   105.8 2722.64
   107.1 2723.64   108.8 2725.15   115.8 2730.91   120.2 2733.58   125.3 2736.33
#Mann= 3 ,0,0
       0     .06       0   32.76    .045       0      48      .1       0
Bank Sta=32.76,48
XS Rating Curve= 0 ,0
Exp/Cntr(USF)=0,0
Exp/Cntr=0.3,0.1

Type RM Length L Ch R = 1 ,1408    ,69.6,75.5,83
BEGIN DESCRIPTION:
IFA added to uncross 500 and 101 profiles
END DESCRIPTION:
XS GIS Cut Line= 3
2298266.47761502556216.3813009162298262.18373455556157.995328603
 2298212.7623855556082.915935707
#Sta/Elev= 30
       0 2717.64     5.1 2717.25    11.2 2716.38    15.2 2715.67    19.3 2714.53
    23.3 2712.56    26.9 2711.07    31.3 2710.25    35.3 2709.97    39.3 2709.41
    43.3 2708.65    55.4  2709.2    59.5 2709.26    66.4  2708.3    69.1 2707.99
    73.9 2707.87    77.9 2708.24      84 2709.96    89.5 2710.91      93 2711.86
    97.8 2712.52   103.9 2712.63   107.4 2712.82   112.6 2713.81     117 2715.28
   121.8 2717.72   126.6 2720.98   129.9 2723.77   136.1 2728.58   148.4 2737.34
#Mann= 4 ,-1,0
       0     .06       0    11.2      .1       0    66.4    .045       0
    77.9      .1       0
#XS Ineff= 2 , 0
           31.91 2715.99
Permanent Ineff=
       F       F
Bank Sta=66.4,77.9
XS Rating Curve= 0 ,0
Exp/Cntr(USF)=0,0
Exp/Cntr=0.3,0.1

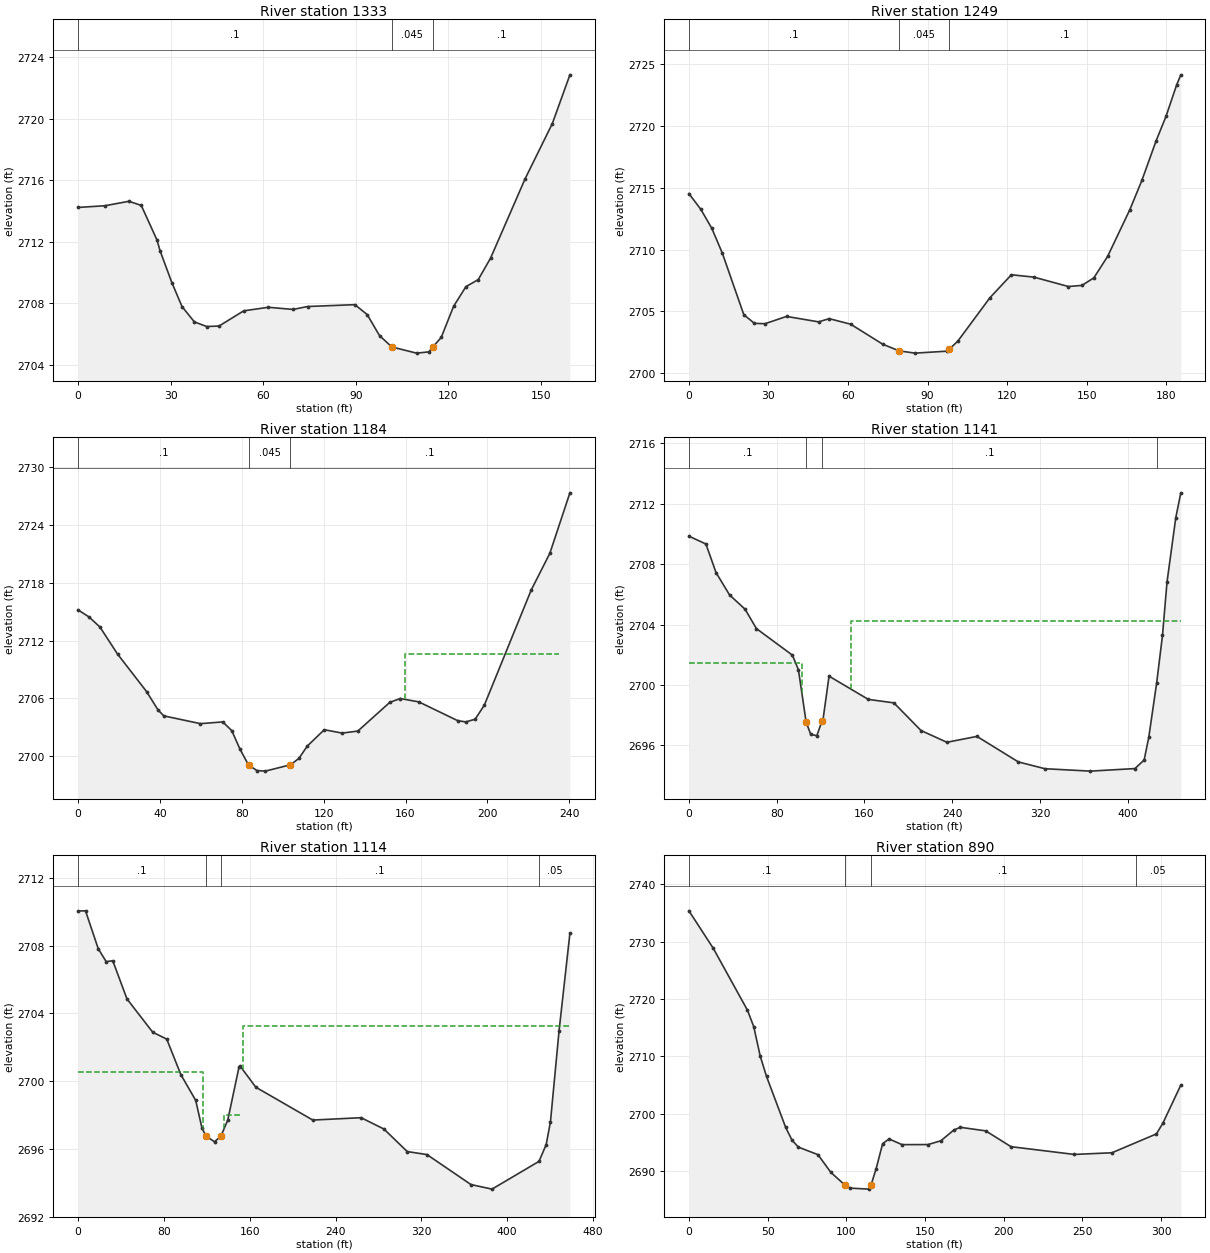
Type RM Length L Ch R = 1 ,1333    ,87.5,84,80
XS GIS Cut Line= 3
2298306.94590326556211.7351725662298319.43151578556188.277355097
2298319.43151578556055.475840069
#Sta/Elev= 30
       0 2714.24     8.7 2714.35    16.5 2714.64    20.5 2714.37    25.6 2712.12
    26.6 2711.42    30.4 2709.36    33.7  2707.8    37.7  2706.8    41.7  2706.5
    45.7 2706.53    53.7 2707.52    61.7 2707.75    69.7 2707.61    74.4  2707.8
    89.7 2707.92    93.7 2707.28    97.7 2705.91   101.7 2705.17   109.7 2704.77
   113.7 2704.85  114.94 2705.16   117.7 2705.79   121.7 2707.81   125.7 2709.09
   129.7 2709.55   133.7 2710.95   144.9 2716.11   153.7 2719.69   159.4 2722.86
#Mann= 3 ,0,0
       0      .1       0   101.7    .045       0  114.94      .1       0
Bank Sta=101.7,114.94
XS Rating Curve= 0 ,0
Exp/Cntr(USF)=0,0
Exp/Cntr=0.3,0.1

Type RM Length L Ch R = 1 ,1249    ,66.9,64.4,65
XS GIS Cut Line= 4
2298398.12870987556205.6815422512298405.31739587 556150.44216563
2298395.48024661556080.447065117 2298367.8605583556028.234503653
#Sta/Elev= 30
       0 2714.53     4.5 2713.25     8.6 2711.73    12.6 2709.71    20.7 2704.73
    24.7 2704.03    28.7    2704    36.8 2704.59    48.9 2704.15    52.9 2704.41
      61 2703.96    73.1 2702.34    79.3  2701.8    85.3 2701.62    97.4 2701.78
    98.1 2701.92   101.4 2702.59   113.5  2706.1   121.6 2707.96   130.1 2707.77
   143.1 2707.01   148.2  2707.1   152.7 2707.71   157.9 2709.45   166.3 2713.24
   170.8 2715.59   176.2 2718.81   179.9 2720.77   183.9 2723.31   185.5 2724.14
#Mann= 3 ,-1,0
       0      .1       0    79.3    .045       0    98.1      .1       0
Bank Sta=79.3,98.1
XS Rating Curve= 0 ,0
Exp/Cntr(USF)=0,0
Exp/Cntr=0.3,0.1

Type RM Length L Ch R = 1 ,1184    ,29.3,43.7,55.8
BEGIN DESCRIPTION:
structure xs 4
END DESCRIPTION:
XS GIS Cut Line= 4
2298420.76573976556205.0476531342298469.56768376556152.383360522
2298450.60159018556070.6902369092298409.62679148 555996.68239568
#Sta/Elev= 30
       0 2715.19     5.3 2714.46    10.7 2713.41    19.3  2710.6    33.5  2706.7
    39.1 2704.79    41.9 2704.18    59.8 2703.37    70.7 2703.55    75.1 2702.65
    79.2 2700.69    83.3 2699.08    87.4  2698.5    91.5 2698.44   103.8  2699.1
   107.9 2699.76     112 2701.04   120.3 2702.74     129 2702.39   136.7  2702.6
   152.3 2705.58   157.4 2705.98   166.5 2705.63   185.4 2703.69   189.4 2703.55
     194 2703.83   198.5 2705.29   221.4 2717.25   230.5 2721.06   240.3 2727.34
#Mann= 3 ,-1,0
       0      .1       0    83.3    .045       0   103.8      .1       0
#XS Ineff= 1 ,-1
  159.66  234.832710.611
Permanent Ineff=
       F
Bank Sta=83.3,103.8
XS Rating Curve= 0 ,0
Exp/Cntr(USF)=0,0
Exp/Cntr=0.5,0.3

Type RM Length L Ch R = 1 ,1141    ,28.4,26.8,28.5
BEGIN DESCRIPTION:
structure xs 3
END DESCRIPTION:
XS GIS Cut Line= 6
2298434.55758462556217.4129252942298558.27865417556069.098982584
2298620.70671679 556010.454438912298705.83589309555945.377913027
2298724.37513593555906.0293159822298722.86172835555888.625128827
#Sta/Elev= 30
       0 2709.86    15.5 2709.34    24.7 2707.45      37 2705.97    51.2 2705.02
    61.5 2703.74    94.3 2701.98    99.8 2701.01   106.82697.557     111 2696.73
   116.6 2696.65   121.3 2697.62   122.2 2697.71   127.7 2700.59   163.5 2699.05
   186.8 2698.82   211.5 2696.99   235.1 2696.21   262.5  2696.6   300.2 2694.91
   324.4 2694.46   365.9  2694.3   406.5 2694.47   414.9 2695.04   419.1 2696.54
   426.3 2700.15   431.6 2703.29   435.7 2706.81   443.7 2711.08   448.3 2712.73
#Mann= 4 ,-1,0
       0      .1       0   106.8    .045       0   121.3      .1       0
   426.2     .05       0
#XS Ineff= 3 ,-1
       0     103 2701.47   124.3  145.07 2698.33  147.61   448.32704.262
Permanent Ineff=
       F       F       F
Bank Sta=106.8,121.3
XS Rating Curve= 0 ,0
Exp/Cntr(USF)=0,0
Exp/Cntr=0.5,0.3

Type RM Length L Ch R = 1 ,1114    ,234.4,224.2,209.9
BEGIN DESCRIPTION:
structure xs 2
END DESCRIPTION:
XS GIS Cut Line= 6
2298448.93495661556229.898537818 2298599.1406588556064.180407953
2298702.05237415555972.2408975492298729.29371056555934.405708082
2298738.37415603555909.4344830342298739.50921172555887.111721248
#Sta/Elev= 30
       0 2710.05       7 2710.06    18.8 2707.83    26.2 2707.06    32.4 2707.11
    45.6 2704.86    69.6 2702.89    82.7 2702.48    95.8 2700.39   109.7 2698.86
   115.5 2697.23   119.32696.751   127.2 2696.42   133.1 2696.74   139.6 2697.71
     150 2700.82   151.3 2700.87   165.7 2699.64   218.8  2697.7   263.8 2697.84
   285.1 2697.17   306.8 2695.84   325.2 2695.66   366.2 2693.89   385.8 2693.62
   429.6 2695.26   436.3 2696.25   440.3 2697.61   448.3 2702.98   458.4 2708.73
#Mann= 4 ,-1,0
       0      .1       0   119.3    .045       0   133.1      .1       0
   429.6     .05       0
#XS Ineff= 3 ,-1
       0   116.3 2700.55   136.1  150.99    2698  153.52   458.42703.281
Permanent Ineff=
       F       F       F
Bank Sta=119.3,133.1
XS Rating Curve= 0 ,0
Exp/Cntr(USF)=0,0
Exp/Cntr=0.5,0.3

Type RM Length L Ch R = 1 ,890     ,73.5,74.4,75.3
BEGIN DESCRIPTION:
strictire xs 1
END DESCRIPTION:
XS GIS Cut Line= 4
2298764.48043677556198.1169786662298757.29175077556137.959027414
2298730.80711814556027.8586260652298744.80613824555889.760184511
#Sta/Elev= 30
       0  2735.4    15.5 2728.85    37.2 2718.07    41.2 2715.19    45.3 2710.08
    49.3 2706.53    61.4 2697.69    65.5 2695.41    69.6 2694.19      82 2692.88
    90.2 2689.79    99.32687.534   102.5 2687.05   114.3 2686.87  115.64 2687.51
     119 2690.46   123.1  2694.8   127.2 2695.62   135.4 2694.63   151.9 2694.64
   160.1  2695.3   168.4 2697.19   172.5 2697.65   188.6 2697.03   204.7 2694.27
   244.9 2692.92   268.8 2693.21   297.1  2696.5   301.2 2698.37   312.6 2705.02
#Mann= 4 ,-1,0
       0      .1       0    99.3    .045       0  115.64      .1       0
  283.83     .05       0
Bank Sta=99.3,115.64
XS Rating Curve= 0 ,0
Exp/Cntr(USF)=0,0
Exp/Cntr=0.3,0.1