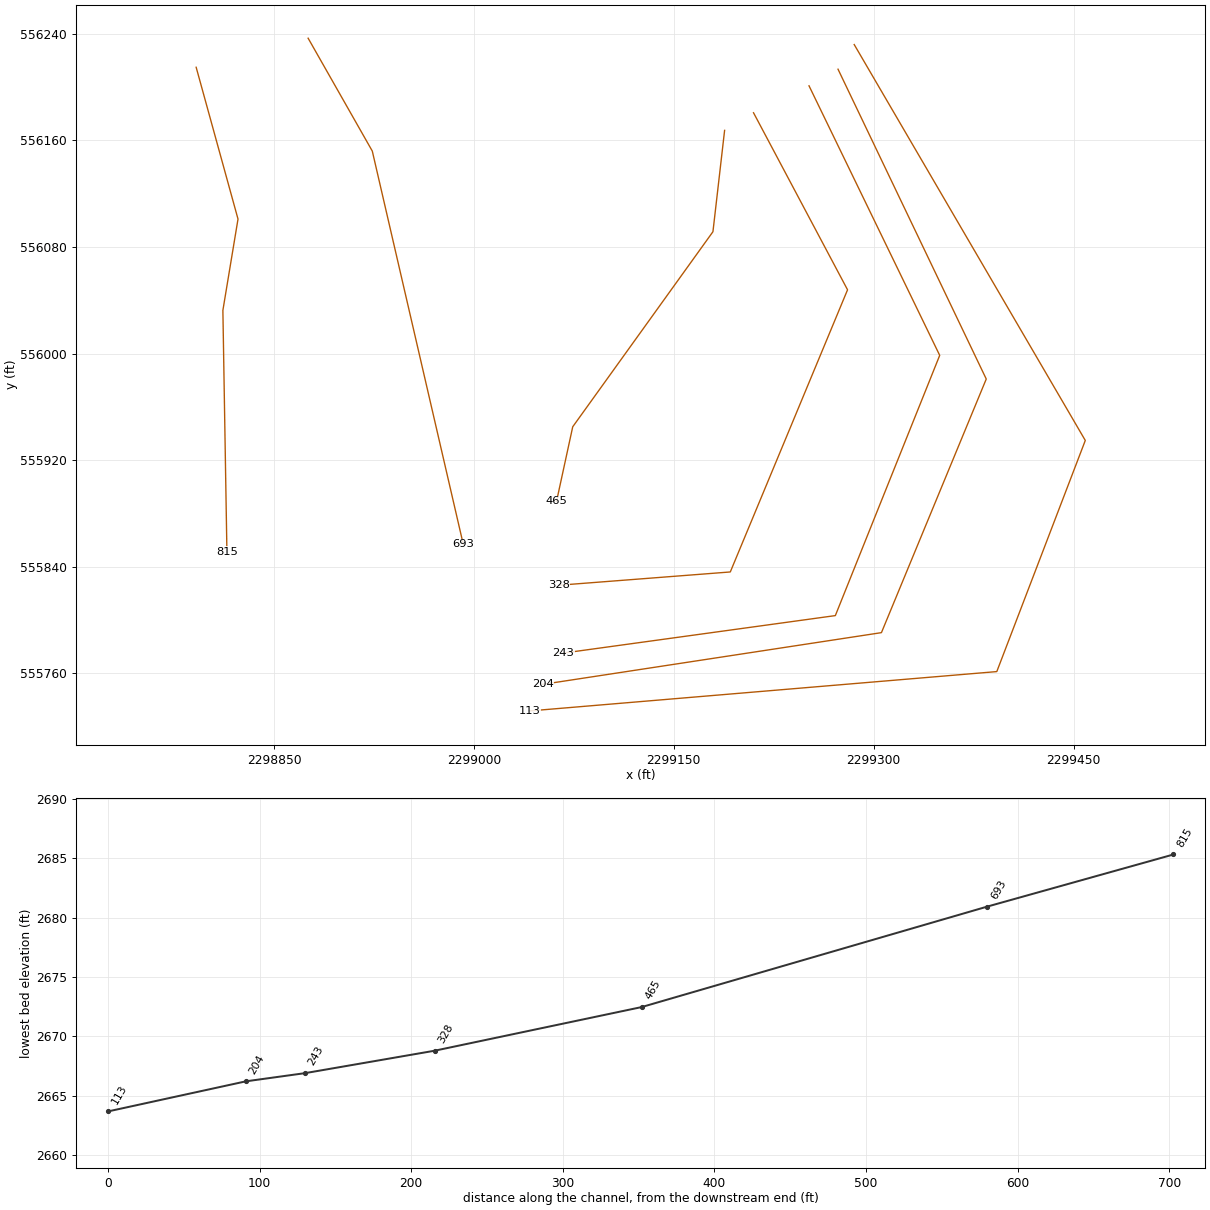
HEC-RAS study ELKCK.prj: ELKCK

--- ELKCK.g01 (geometry) --- (continued)

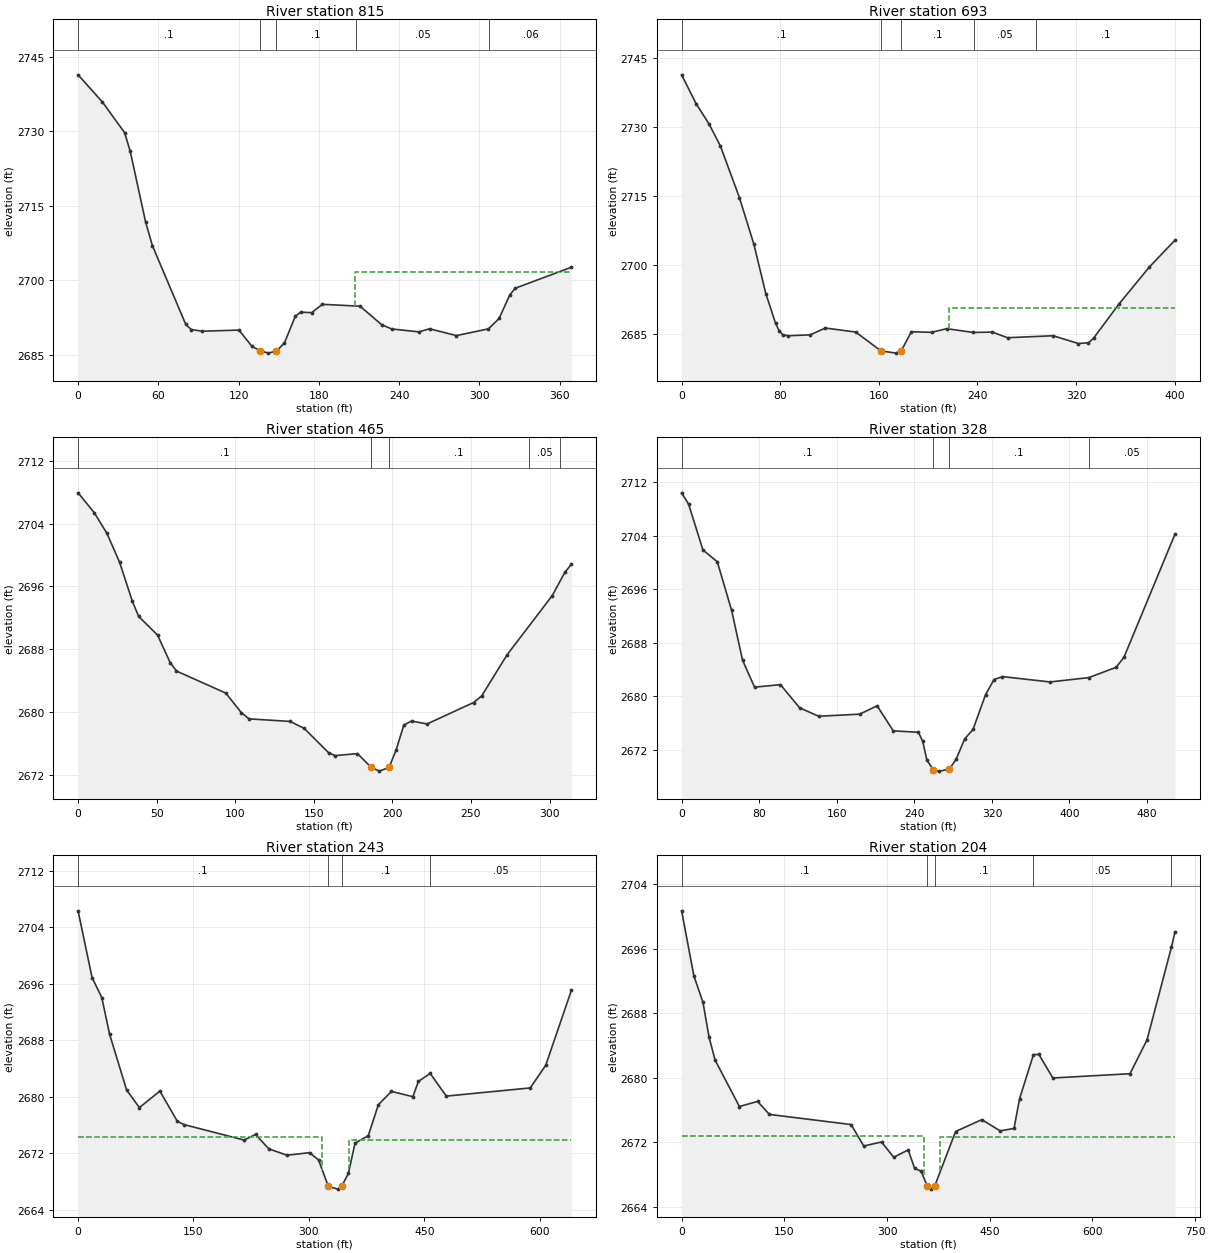
Type RM Length L Ch R = 1 ,815     ,117.2,122.7,126.8
XS GIS Cut Line= 4
2298791.61468032556214.7619877232298823.01788758556100.878067429
2298811.66733074556032.396374495 2298814.6941459 555851.16581695
#Sta/Elev= 30
       0 2741.32    18.2 2735.85    34.8 2729.68      39 2725.92    50.5 2711.69
    55.6 2706.93    80.5 2691.11    84.6 2690.08    92.9 2689.74   120.3 2689.97
     130 2686.69   136.12685.833   142.2 2685.33   148.3 2685.76   154.3 2687.39
   162.4 2692.74   166.5 2693.58   174.6 2693.47   182.7 2695.15   210.8 2694.77
   226.9 2691.06   234.5 2690.19   254.8 2689.61   262.8 2690.23   282.8 2688.86
   306.8 2690.21   314.8 2692.31   322.8 2697.06   326.8 2698.38   368.8 2702.61
#Mann= 5 ,-1,0
       0      .1       0   136.1    .045       0   148.3      .1       0
  207.55     .05       0  307.55     .06       0
#XS Ineff= 2 , 0
                          206.87         2701.63
Permanent Ineff=
       F       F
Bank Sta=136.1,148.3
XS Rating Curve= 0 ,0
Exp/Cntr(USF)=0,0
Exp/Cntr=0.3,0.1

Type RM Length L Ch R = 1 ,693     ,240,228.1,218.3
XS GIS Cut Line= 3
2298875.64284897556236.557297251 2298923.7917082 556151.88171724
2298992.04871169 555856.90077511
#Sta/Elev= 30
       0 2741.26    11.7 2735.03    22.3 2730.59    31.5 2725.81    46.9 2714.65
    58.6 2704.56    68.3 2693.86    76.2 2687.41    79.1 2685.83    82.1 2684.88
    86.7 2684.71   104.3  2684.9   116.6 2686.38   141.2 2685.51   161.8 2681.41
   174.1 2680.94   178.2 2681.45   186.4 2685.57   202.8 2685.45   215.1 2686.24
   236.7 2685.42   252.1  2685.5   264.4 2684.28   301.4 2684.71   321.9 2683.02
   330.1 2683.19   334.2 2684.18   354.7 2691.54   379.4 2699.58   400.2  2705.4
#Mann= 5 ,-1,0
       0      .1       0   161.8    .045       0   178.2      .1       0
  237.41     .05       0  287.41      .1       0
#XS Ineff= 2 , 0
                          216.82         2690.62
Permanent Ineff=
       F       F
Bank Sta=161.8,178.2
XS Rating Curve= 0 ,0
Exp/Cntr(USF)=0,0
Exp/Cntr=0.3,0.1

Type RM Length L Ch R = 1 ,465     ,134.4,136.5,139.4
XS GIS Cut Line= 4
2299188.17699724556167.414281019 2299179.4251901556091.391008252
2299074.20586636 555945.054424832299062.07224048555889.181958678
#Sta/Elev= 30
       0 2707.91    10.3 2705.38    18.4 2702.73    26.4 2699.07    34.5 2694.12
    38.5 2692.18    50.6 2689.78    58.6 2686.29    62.6 2685.21      94  2682.4
   103.9 2679.91   108.8 2679.12   134.9 2678.79   143.8 2677.92   159.6 2674.77
   163.6 2674.44   177.8 2674.69   186.5 2672.95   191.7 2672.46   197.9 2672.93
   202.4 2675.16   207.3 2678.33   212.2 2678.84   222.1 2678.47   251.7  2681.2
   256.8 2682.03     273 2687.28   301.7 2694.81   309.8 2697.79   313.9  2698.8
#Mann= 5 ,-1,0
       0      .1       0   186.5    .045       0   197.9      .1       0
  286.76     .05       0  306.76      .1       0
Bank Sta=186.5,197.9
XS Rating Curve= 0 ,0
Exp/Cntr(USF)=0,0
Exp/Cntr=0.3,0.1

Type RM Length L Ch R = 1 ,328     ,84.7,85.4,85.2
BEGIN DESCRIPTION:
structure xs 4
END DESCRIPTION:
XS GIS Cut Line= 4
2299209.87593805556180.6363534912299280.43892139556047.811914257
 2299192.4427304 555836.122964232299063.76905489555826.161131287
#Sta/Elev= 30
       0 2710.41     7.2 2708.71      22 2701.86    36.8  2700.1    51.6 2692.81
    62.8 2685.39    75.2 2681.34   101.9 2681.72   121.7 2678.25   141.3 2676.99
   183.6  2677.3   201.6 2678.55   218.2 2674.81   244.2 2674.59   248.6 2673.25
   252.9 2670.46   259.7 2668.94   265.7 2668.78   276.1 2669.06   283.2 2670.59
   291.9  2673.6   300.5 2675.01   313.5 2680.24   322.2 2682.48   330.9 2682.92
   379.9 2682.12   419.9 2682.77   448.1 2684.31   456.2 2685.82   508.7  2704.2
#Mann= 4 ,-1,0
       0      .1       0   259.7    .045       0   276.1      .1       0
   419.9     .05       0
Bank Sta=259.7,276.1
XS Rating Curve= 0 ,0
Exp/Cntr(USF)=0,0
Exp/Cntr=0.5,0.3

Type RM Length L Ch R = 1 ,243     ,38.5,39,38.6
BEGIN DESCRIPTION:
structure xs 3
END DESCRIPTION:
XS GIS Cut Line= 4
2299251.51871394556200.8579347522299349.59327784555998.622851509
2299271.27288095555803.3801307572299067.18727943555775.262711488
#Sta/Elev= 30
       0 2706.32    18.2 2696.86    30.8 2694.04      41 2688.82    63.1 2680.93
    79.7 2678.44   106.3 2680.78     129  2676.5   137.5 2676.04   215.8 2673.84
   230.6 2674.63   247.9  2672.6   271.5 2671.69   300.8 2672.06   312.5 2671.03
   325.3 2667.27   337.7 2666.89   342.7 2667.32   351.3 2669.11   359.9 2673.39
   377.2 2674.48   390.3 2678.86   407.3 2680.73   435.1 2679.99   442.3 2682.15
   457.6 2683.28   478.6 2680.07   587.7 2681.23   607.8 2684.44   641.1 2695.05
#Mann= 4 ,-1,0
       0      .1       0   325.3    .045       0   342.7      .1       0
   457.6     .05       0
#XS Ineff= 2 , 0
           317.6  2674.3  352.38          2673.9
Permanent Ineff=
       F       F
Bank Sta=325.3,342.7
XS Rating Curve= 0 ,0
Exp/Cntr(USF)=0,0
Exp/Cntr=0.5,0.3

Type RM Length L Ch R = 1 ,204     ,89.9,91,91.8
BEGIN DESCRIPTION:
structure xs 2
END DESCRIPTION:
XS GIS Cut Line= 4
2299273.28601393556213.3130203862299384.52648179555980.870251728
2299305.86859185555790.5950923952299051.84792518555751.812496999
#Sta/Elev= 30
       0 2700.73    17.9 2692.66    31.2 2689.38    40.1 2685.05    48.9 2682.21
    84.4 2676.45     111 2677.08   128.2 2675.47   247.6 2674.21     266 2671.55
     292 2672.05   309.8 2670.15   330.9 2671.07   340.4 2668.76   349.6 2668.45
   358.8  2666.6   364.9  2666.2   369.9 2666.64   400.2 2673.35   438.4 2674.82
   465.3 2673.43   485.5 2673.73   493.6 2677.41   513.9 2682.89   521.9 2682.91
   542.2 2679.99   654.9 2680.52   679.8 2684.72   715.5 2696.25   720.5 2698.06
#Mann= 5 ,-1,0
       0      .1       0   358.8    .045       0   369.9      .1       0
   513.9     .05       0   715.5     .07       0
#XS Ineff= 2 , 0
           353.6 2672.77  378.12         2672.72
Permanent Ineff=
       F       F
Bank Sta=358.8,369.9
XS Rating Curve= 0 ,0
Exp/Cntr(USF)=0,0
Exp/Cntr=0.5,0.3

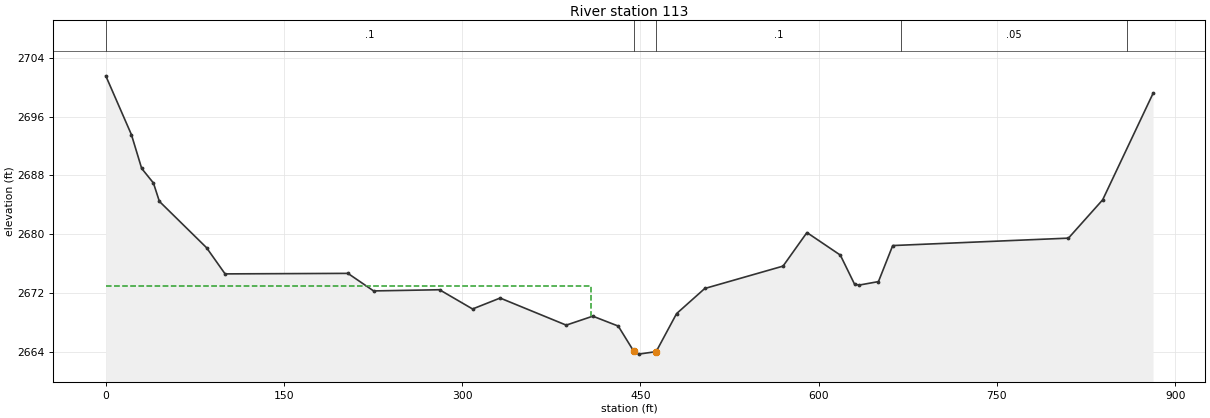
Type RM Length L Ch R = 1 ,113     ,,,
XS GIS Cut Line= 4
2299285.43916807556231.7958269612299458.84885263555934.785622564
2299392.43663301555761.3759380092299041.92769615555731.859395957
#Sta/Elev= 30
       0 2701.57    21.6 2693.55    30.2 2688.96    40.1 2686.97    45.1 2684.47
    84.8 2678.16   100.4 2674.59   203.8 2674.66   225.4 2672.27   280.9 2672.43
   308.7 2669.81   331.9  2671.3   387.5 2667.61   409.9 2668.83   431.3 2667.48
   444.2 2664.09   448.4 2663.66   463.2    2664   480.4 2669.18   504.1  2672.6
     570 2675.65   590.1 2680.22   618.2 2677.15   630.2 2673.18   634.2 2673.07
   650.3 2673.54   662.3 2678.45   810.2 2679.46     839 2684.68   881.4 2699.18
#Mann= 5 ,-1,0
       0      .1       0   444.2    .045       0   463.2      .1       0
  669.62     .05       0  859.62     .07       0
#XS Ineff= 2 , 0
          408.22 2672.95
Permanent Ineff=
       F       F
Bank Sta=444.2,463.2
XS Rating Curve= 0 ,0
Exp/Cntr(USF)=0,0
Exp/Cntr=0.3,0.1
LCMann Table=0

Chan Stop Cuts=-1
Use User Specified Reach Order=0
Composite Channel Slope=5